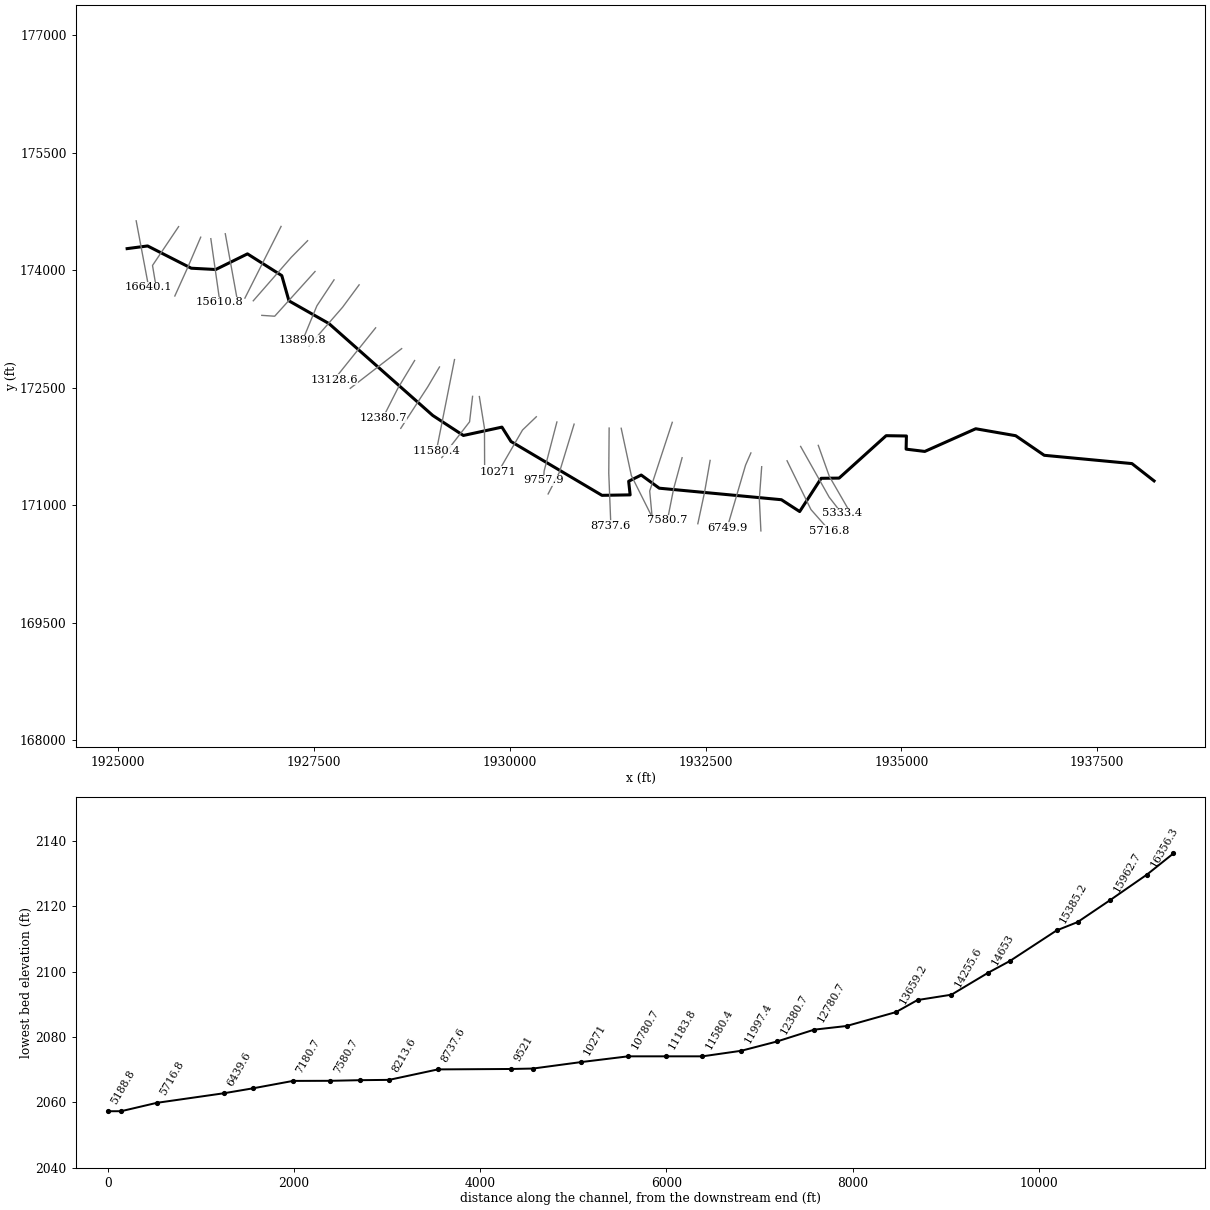
--- WlfCrk.prj (project) ---

Proj Title=WlfCrk
Current Plan=p01
Default Exp/Contr=0,0
English Units
Geom File=g01
Flow File=f01
Plan File=p01
BEGIN DESCRIPTION:
END DESCRIPTION:
DSS Export Rating Curves= 0
DSS Export Rating Curve Sorted= 0
DSS Export Volume Flow Curves= 0
DXF OffsetX= 0
DXF OffsetY= 0
DXF ScaleX= 0
DXF ScaleY= 0

--- WlfCrk.p01 (plan) ---

Plan Title=Floodplain
Program Version=4.00
Geom File=g01
Flow File=f01
K Sum by GR=0
Std Step Tol=0.01
Critical Tol=0.01
Num of Std Step Trials=20
Max Error Tol=0.3
Flow Tol Ratio=0.001
Split Flow NTrial=30
Split Flow Tol=0.02
Split Flow Ratio=0.02
Log Output Level=0
Friction Slope Method=1
Unsteady Friction Slope Method=2
Unsteady Bridges Friction Slope Method=1
Global Log Level=0
CheckData=False
Run HTab=0
Run UNet=0
Run PostProcess=0
UNET Theta=0
UNET Theta Warmup=0
UNET ZTol=0
UNET ZSATol=0
UNET MxIter=0
UNET MaxInSteps=0
UNET DtIC=0
UNET DtMin=0
UNET MaxCRTS=0
UNET WFStab=0
UNET SFStab=0
UNET WFX=0
UNET SFX=0
UNET DSS MLevel=0
UNET DZMax Abort=0
UNET Convert EG Bridges=0
UNET Use Existing IB Tables=0
UNET Froude Limit=0
UNET Froude Power=0
Write IC File=0
Echo Input=False
Echo Output=False
Write Detailed=0

--- WlfCrk.f01 (steady flow) ---

Flow Title=NFF Regression Equation
Program Version=4.00
Number of Profiles=1
Profile Names=P100yr
River Rch & RM=WlfCrk,Main      ,16640.1
517.1070
River Rch & RM=WlfCrk,Main      ,16356.3
519.1744
River Rch & RM=WlfCrk,Main      ,15962.7
588.3161
River Rch & RM=WlfCrk,Main      ,14255.6
643.7556
River Rch & RM=WlfCrk,Main      ,11183.8
711.4256
River Rch & RM=WlfCrk,Main      ,10780.7
792.4283
River Rch & RM=WlfCrk,Main      ,9757.9
801.7101
River Rch & RM=WlfCrk,Main      ,7898.7
887.7087
River Rch & RM=WlfCrk,Main      ,7580.7
1096.914
River Rch & RM=WlfCrk,Main      ,394.9
1208.645
Boundary for River Rch & Prof#=WlfCrk,Main      ,1
Up Type=0
Dn Type=3
Dn Slope=0.032214

--- WlfCrk.g01 (geometry) ---

Geom Title=USGS 3m DEM
Program Version=4.10

River Reach=WlfCrk          ,Main
Reach XY= 30
     1925113.089       174274.69     1925374.443      174308.721
     1925932.017      174024.486     1926244.425      174008.067
     1926649.693      174207.646     1927088.024      173930.125
     1927179.425      173607.802     1927690.355      173317.686
     1929016.314      172143.751      1929406.92       171888.67
     1929899.127      171995.313     1930015.012      171811.719
     1931176.471      171124.219     1931536.314      171130.091
     1931517.616      171303.907     1931677.773      171383.334
     1931908.241      171215.365     1933468.137       171068.23
      1933701.21      170917.188     1933975.885      171341.711
     1934205.116      171344.271     1934805.377      171885.938
     1935064.492      171882.032     1935060.585      171714.063
     1935298.975      171684.802     1935949.439      171974.509
     1936459.482      171885.609     1936824.156      171635.519
     1937944.243       171529.62     1938226.896      171308.673

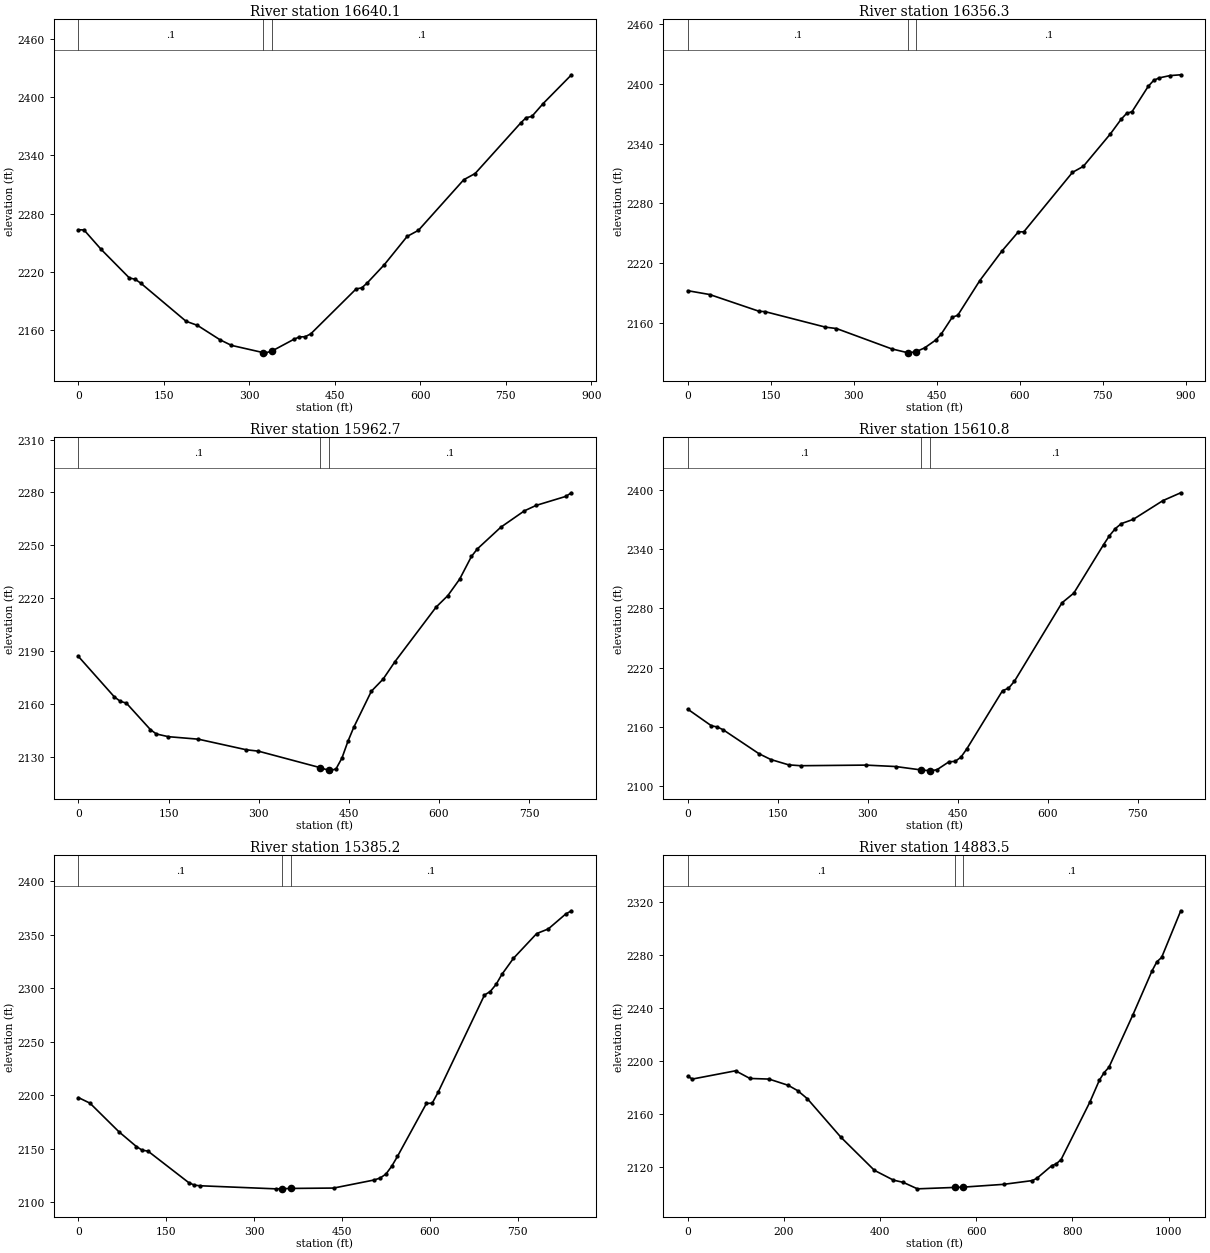
Type RM Length L Ch R = 1 ,16640.1 ,302.1,283.7,265.4
XS GIS Cut Line= 2
     1925228.639      174629.722     1925388.757      173779.621
#Sta/Elev= 30
       0 2263.27     9.9 2263.03    39.8 2243.07    89.5 2213.46    99.4 2212.22
   109.4 2208.14   188.9 2168.77   208.8 2164.57   248.6 2149.62   268.5  2143.9
     324 2136.45   328.1 2136.19     339 2137.88   377.8  2150.1   387.8 2152.65
   397.7  2152.8   407.7 2155.81   487.2 2202.17   497.2  2203.3   507.1 2208.62
   536.9 2227.36   576.7 2256.37   596.6 2262.72   676.1 2314.95     696 2321.33
   775.6 2373.32   785.5 2379.01   795.4 2380.22   815.3 2393.56     865 2423.26
#Mann= 3 , 0 , 0
       0      .1       0     324    .045       0     339      .1       0
Bank Sta=324,339
XS Rating Curve= 0 ,0
Exp/Cntr=0.3,0.1

Type RM Length L Ch R = 1 ,16356.3 ,389.3,393.6,397.5
XS GIS Cut Line= 3
      1925770.33      174555.675     1925437.104      174059.698
     1925485.815      173770.425
#Sta/Elev= 30
       0 2192.21    39.8 2188.35   129.5 2171.41   139.4 2171.22     249 2155.56
   268.9 2154.16   368.5 2133.74   397.6 2129.83   398.4 2129.73   412.6 2130.85
   428.2 2134.74   448.1 2142.54   458.1 2148.58     478  2165.5     488  2167.5
   527.8 2202.35   567.6 2231.92   597.5 2251.39   607.3 2251.37   695.3 2311.16
   714.9  2317.2   763.8 2349.84   783.3 2364.64   793.1 2370.41   802.9 2372.19
   832.2 2397.69     842 2403.61   851.8 2406.09   871.3 2408.41   890.9 2409.24
#Mann= 3 , 0 , 0
       0      .1       0   397.6    .045       0   412.6      .1       0
Bank Sta=397.6,412.6
XS Rating Curve= 0 ,0
Exp/Cntr=0.3,0.1

Type RM Length L Ch R = 1 ,15962.7 ,339.2,351.9,365
XS GIS Cut Line= 3
     1926052.508      174420.702     1925891.324      174044.602
     1925722.087      173669.743
#Sta/Elev= 30
       0  2186.9    59.9 2163.91    69.9 2161.38    79.8 2160.41   119.8 2145.37
   129.7 2142.88   149.7 2141.34   199.6 2139.92   279.4 2133.91   299.4 2133.13
   401.7 2123.82   416.7 2122.23     419 2121.95   428.8 2123.13   438.6 2129.23
   448.4 2138.61   458.2 2146.65   487.5 2167.14   507.1 2174.04   526.7  2183.9
   595.2 2214.88   614.8 2221.44   634.4 2230.76     654 2243.63   663.8 2247.91
     703 2260.27   742.1 2269.53   761.7 2272.63   810.7  2277.7   820.5 2279.79
#Mann= 3 , 0 , 0
       0      .1       0   401.7    .045       0   416.7      .1       0
Bank Sta=401.7,416.7
XS Rating Curve= 0 ,0
Exp/Cntr=0.3,0.1

Type RM Length L Ch R = 1 ,15610.8 ,227,225.6,224.2
XS GIS Cut Line= 2
     1926181.864      174401.483     1926297.869      173587.884
#Sta/Elev= 30
       0 2177.84    39.6 2160.89    49.5  2159.7    59.4 2156.78   118.8 2132.59
   138.6 2126.67   168.3 2121.26   188.1 2120.38     297    2121   346.6 2119.56
   389.6 2116.05   404.6 2115.23     406 2115.18   415.9 2116.48   435.7 2124.44
   445.6  2124.7   455.5 2129.09   465.4 2137.64   524.8 2196.58   534.7 2198.97
   544.6 2206.11   623.8 2285.66   643.6 2295.58   693.1 2344.68     703 2353.85
   712.9 2361.12   722.8  2366.1   742.6  2370.4   792.1 2389.45   821.8 2397.39
#Mann= 3 , 0 , 0
       0      .1       0   389.6    .045       0   404.6      .1       0
Bank Sta=389.6,404.6
XS Rating Curve= 0 ,0
Exp/Cntr=0.3,0.1

Type RM Length L Ch R = 1 ,15385.2 ,514.5,501.7,488.8
XS GIS Cut Line= 2
     1926366.412      174464.585     1926516.654      173636.422
#Sta/Elev= 30
       0 2197.81    19.8 2192.57    69.3 2165.84      99 2152.11   108.9 2148.69
   118.8 2147.83   188.1 2118.52     198 2116.04   207.9 2115.49   336.7 2112.62
     348 2112.72     363    2113   435.7 2113.35     505  2120.9   514.9 2122.69
   524.8 2126.32   534.7 2133.58   544.6 2142.84   594.1 2192.33     604 2192.59
   613.9 2202.61   693.2 2293.53     703 2296.78     713 2303.42   722.8  2312.7
   742.7  2327.8   782.3 2350.87   802.1 2355.19   831.8 2369.11   841.7 2372.14
#Mann= 3 , 0 , 0
       0      .1       0     348    .045       0     363      .1       0
Bank Sta=348,363
XS Rating Curve= 0 ,0
Exp/Cntr=0.3,0.1

Type RM Length L Ch R = 1 ,14883.5 ,236.3,230.2,224.1
XS GIS Cut Line= 2
     1927078.772      174558.062     1926616.992       173642.61
#Sta/Elev= 30
       0 2188.31      10 2186.24    99.6 2192.47   129.4 2186.68   169.2 2186.21
     209 2181.51     229  2177.4   248.9 2171.37   318.6 2142.28   388.2 2117.28
     428 2109.83     448  2108.2   477.8 2103.27   556.7 2104.36   571.7 2104.53
     657 2106.67   716.7 2109.51   726.7  2111.4   756.6 2120.64   766.5 2122.17
   776.5 2125.42   836.2 2168.75   856.1 2185.39     866 2191.11     876 2195.16
   925.8 2234.77   965.6    2268   975.6 2274.84   985.5 2278.11  1025.3 2313.38
#Mann= 3 , 0 , 0
       0      .1       0   556.7    .045       0   571.7      .1       0
Bank Sta=556.7,571.7
XS Rating Curve= 0 ,0
Exp/Cntr=0.3,0.1

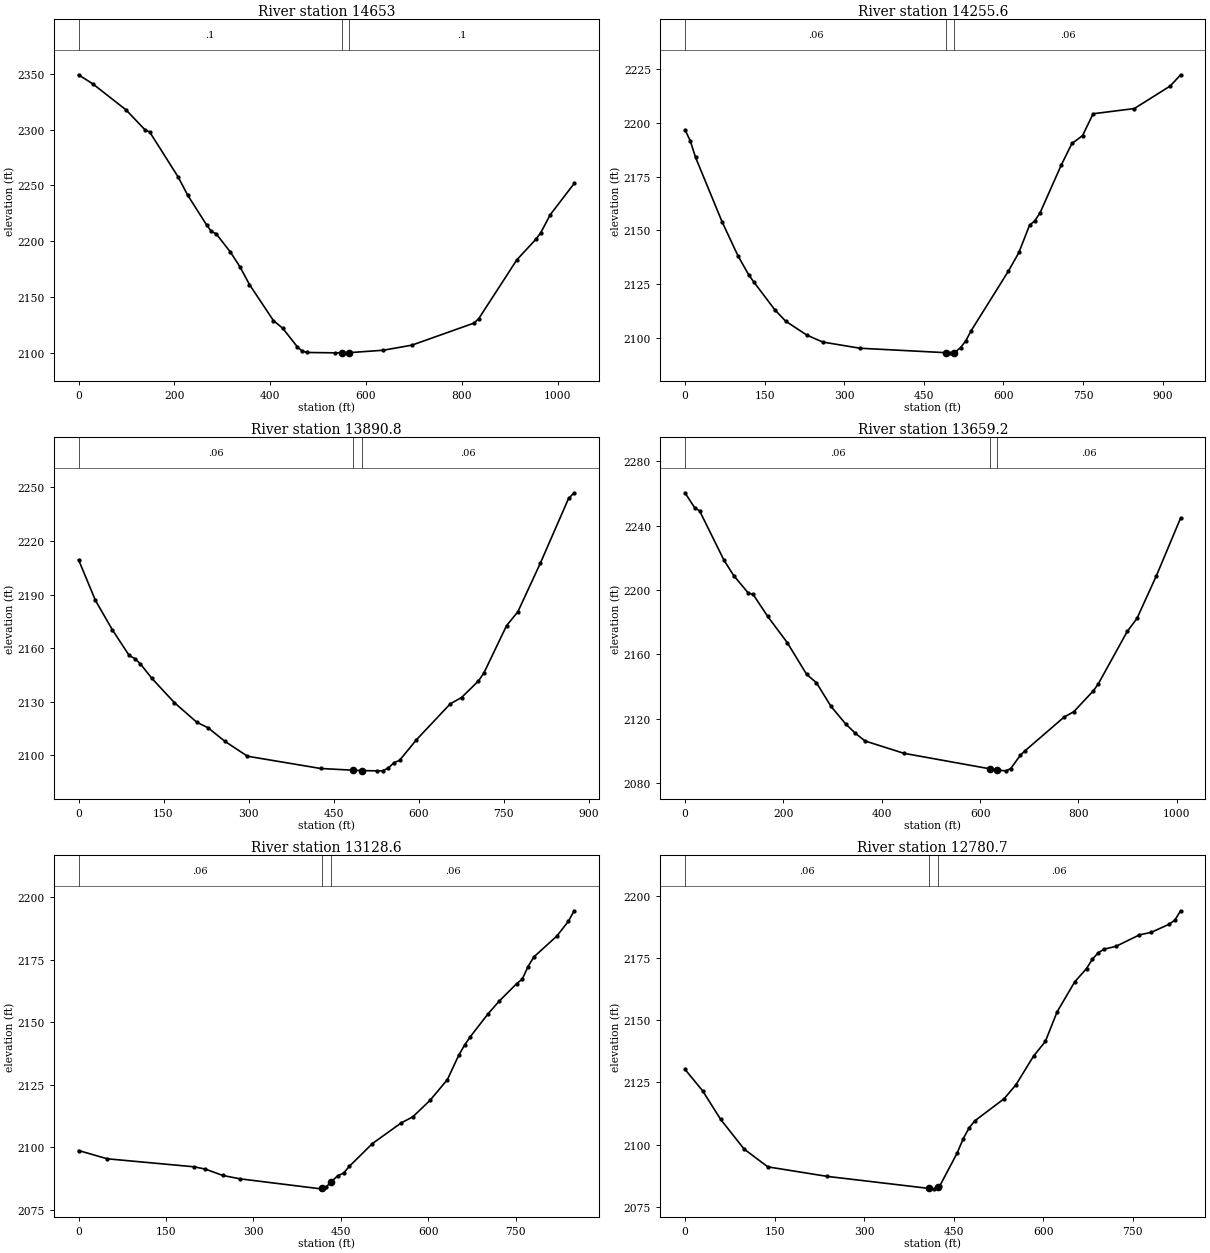
Type RM Length L Ch R = 1 ,14653   ,397.2,397.4,397.6
XS GIS Cut Line= 3
     1927417.528      174375.654     1927209.063      174163.931
     1926723.752      173608.513
#Sta/Elev= 30
       0 2349.28    29.7 2341.15      99 2317.87   138.7 2299.92   148.6  2297.9
     208 2257.56   227.8 2241.32   267.4  2214.5   277.3 2208.71   287.2 2206.67
   317.1 2190.16     337 2176.95   356.9    2161   406.8 2128.74   426.7 2121.61
   456.6 2105.23   466.6 2101.35   476.5 2100.05   536.3 2099.73   549.9 2099.79
   564.9 2099.89     636 2102.06   695.8 2106.61   825.4  2126.4   835.4 2130.37
   915.1 2183.24     955 2201.78   964.9 2207.48   984.9 2223.77  1034.7 2251.72
#Mann= 3 , 0 , 0
       0      .1       0   549.9    .045       0   564.9      .1       0
Bank Sta=549.9,564.9
XS Rating Curve= 0 ,0
Exp/Cntr=0.3,0.1

Type RM Length L Ch R = 1 ,14255.6 ,357.4,364.8,372.2
XS GIS Cut Line= 3
     1927512.708      173982.483      1926997.34        173411.5
      1926832.78      173422.422
#Sta/Elev= 30
       0 2196.86      10 2191.67      20 2183.95    69.9 2153.98    99.9 2138.14
   119.9 2129.37   129.9 2125.88   169.8 2112.86   189.8  2107.7   229.8 2101.19
   259.7 2097.98   329.6 2095.11   492.5 2093.02   499.5 2092.96   507.5 2092.97
   519.4 2095.39   529.4 2098.64   539.4  2103.3   609.3 2130.93   629.3 2139.69
   649.3 2152.36   659.3 2154.45   669.3 2158.22   709.2 2180.45   729.2 2190.45
   749.2  2194.1   769.2  2204.3   846.8 2206.71   914.7 2217.26   934.1 2222.45
#Mann= 3 , 0 , 0
       0     .06       0   492.5    .045       0   507.5     .06       0
Bank Sta=492.5,507.5
XS Rating Curve= 0 ,0
Exp/Cntr=0.3,0.1

Type RM Length L Ch R = 1 ,13890.8 ,239,231.6,224.2
XS GIS Cut Line= 3
     1927755.295      173875.718     1927536.021      173544.097
     1927353.839      173103.082
#Sta/Elev= 30
       0 2209.52    29.8 2186.75    59.6 2170.32    89.4 2155.89    99.4 2154.14
   109.3 2151.14   129.2 2143.18     169 2129.54   208.7 2118.51   228.6 2115.42
   258.4 2107.82   298.2 2099.49   427.4 2092.63   484.4 2091.68   499.4 2091.45
   526.8 2091.32   536.7 2091.34   546.7 2092.89   556.6 2095.86   566.6 2097.21
   596.4 2108.73     656  2128.8   675.9 2132.35   705.7 2141.56   715.7 2146.27
   755.4  2172.6   775.3 2180.32   815.1 2207.61   864.8 2243.75   874.7 2246.94
#Mann= 3 , 0 , 0
       0     .06       0   484.4    .045       0   499.4     .06       0
Bank Sta=484.4,499.4
XS Rating Curve= 0 ,0
Exp/Cntr=0.3,0.1

Type RM Length L Ch R = 1 ,13659.2 ,530.5,530.5,531.1
XS GIS Cut Line= 3
     1928075.498      173812.145     1927863.775      173525.505
     1927436.335      173033.914
#Sta/Elev= 30
       0 2260.47    19.8 2251.13    29.7 2249.24    79.2 2218.64      99 2209.05
   128.7 2198.15   138.6 2197.29   168.3 2183.58   207.9 2167.35   247.5 2147.54
   267.3  2142.4     297 2127.67   326.7 2116.79   346.5 2110.96   366.2 2106.18
   445.2 2098.52   620.4 2088.86   635.4 2088.06   652.5 2087.63   662.3 2089.04
   682.1 2097.38   691.9 2100.22   770.9 2121.06   790.6 2124.39   830.1 2137.29
     840 2141.49   899.2 2174.25     919 2182.36   958.4 2208.81  1007.8 2244.81
#Mann= 3 , 0 , 0
       0     .06       0   620.4    .045       0   635.4     .06       0
Bank Sta=620.4,635.4
XS Rating Curve= 0 ,0
Exp/Cntr=0.3,0.1

Type RM Length L Ch R = 1 ,13128.6 ,352.9,347.5,341.5
XS GIS Cut Line= 2
     1928286.245      173263.268     1927754.196      172599.754
#Sta/Elev= 30
       0 2098.72    49.4  2095.4   197.8 2092.21   217.6 2091.29   247.2 2088.76
   276.9 2087.39   415.4 2083.38   417.7 2083.56   425.2 2084.13   432.7 2086.03
     445 2088.65   454.9 2089.68   464.8 2092.41   504.4 2101.51   553.8 2109.78
   573.6 2112.19   603.2  2118.8   632.9 2127.07   652.7 2136.98   662.6 2140.93
   672.5 2144.31   702.2 2153.27   721.9 2158.51   751.6 2165.44   761.5 2167.31
   771.4 2172.35   781.3 2176.17   820.8 2184.54   840.6 2190.45   850.5 2194.65
#Mann= 3 , 0 , 0
       0     .06       0   417.7    .045       0   432.7     .06       0
Bank Sta=417.7,432.7
XS Rating Curve= 0 ,0
Exp/Cntr=0.3,0.1

Type RM Length L Ch R = 1 ,12780.7 ,392.2,399.9,409.6
XS GIS Cut Line= 3
     1928618.521      172997.549     1928288.846      172743.318
     1927961.749      172490.259
#Sta/Elev= 30
       0 2130.28    29.7  2121.6    59.5 2110.24    99.1 2098.21   138.8 2091.09
   237.9 2087.27   408.8 2082.42   416.3 2082.26   423.8 2083.02   426.2 2083.26
   455.7 2096.63   465.6 2102.24   475.4 2106.65   485.2 2109.57   534.5  2118.5
   554.2  2124.1   583.7 2135.61   603.4 2141.49   623.1 2153.39   652.6 2165.44
   672.3 2170.76   682.2 2174.56     692 2177.13   701.9 2178.57   721.6  2179.7
     761 2184.31   780.6 2185.31   810.2 2188.53     820 2190.18   829.9 2193.99
#Mann= 3 , 0 , 0
       0     .06       0   408.8    .045       0   423.8     .06       0
Bank Sta=408.8,423.8
XS Rating Curve= 0 ,0
Exp/Cntr=0.3,0.1

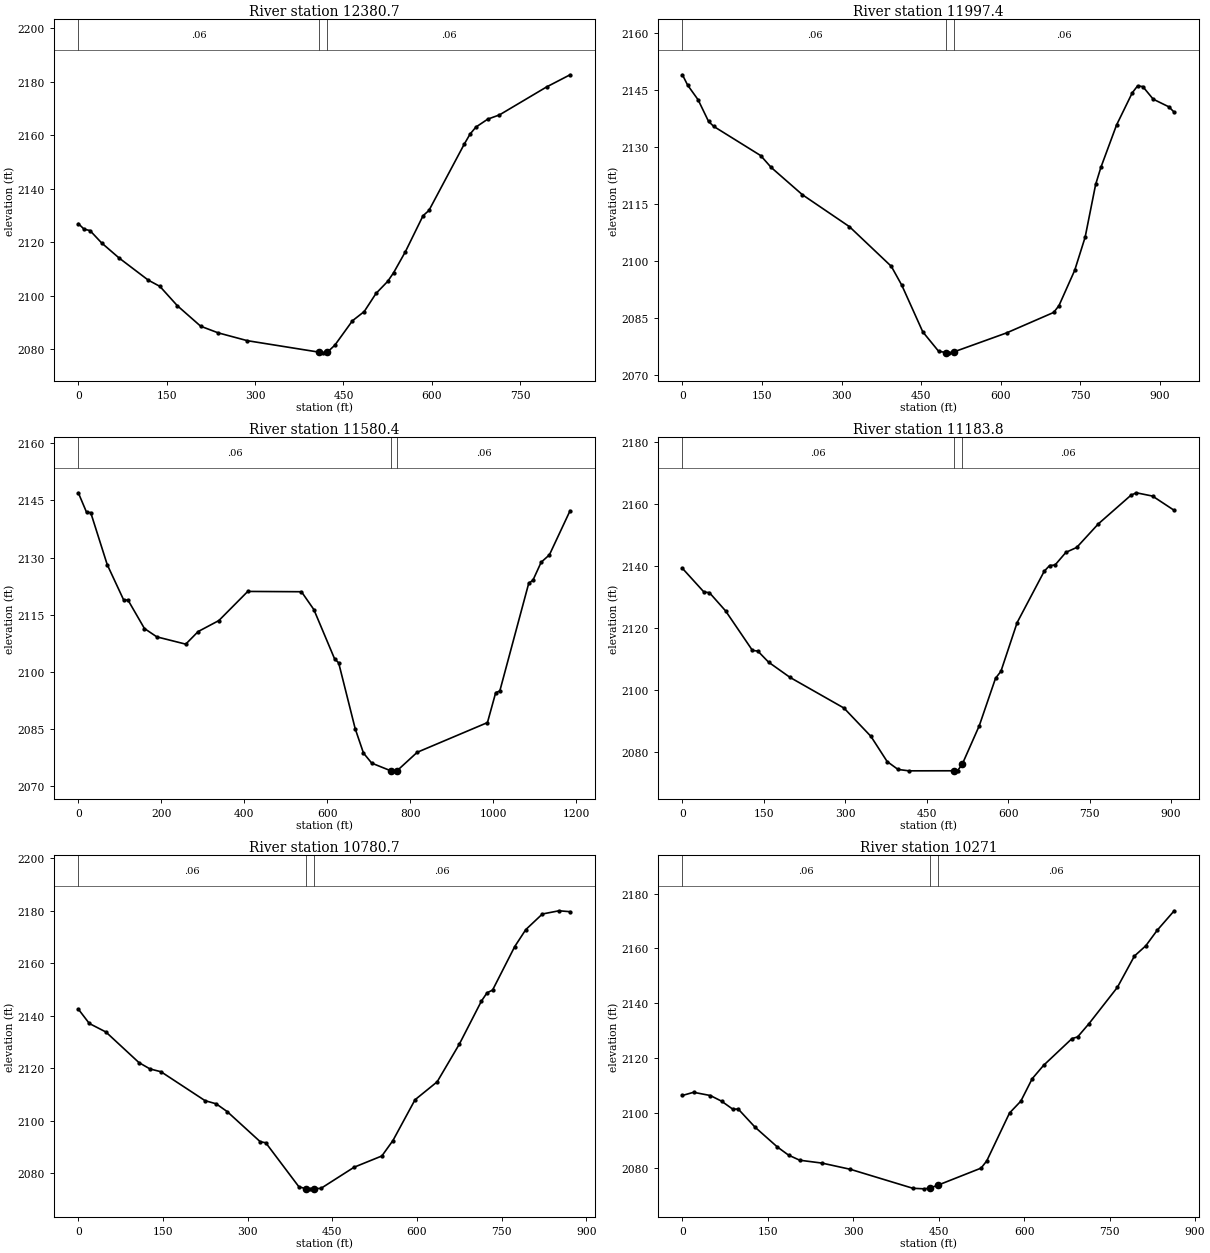
Type RM Length L Ch R = 1 ,12380.7 ,379.4,383.5,382.3
XS GIS Cut Line= 3
     1928784.095      172845.726     1928569.664      172490.008
     1928380.216       172116.16
#Sta/Elev= 30
       0 2126.98     9.9 2124.89    19.8 2124.39    39.6 2119.75    69.2 2114.12
   118.7 2105.84   138.4 2103.51   168.1 2096.26   207.7 2088.59   237.3 2086.12
   286.8 2083.19   407.8 2078.92   415.4 2078.64   422.8 2078.92   435.3  2081.5
   465.2 2090.64   485.2 2094.09   505.2 2100.87   525.1  2105.4   535.1 2108.64
     555 2116.46     585 2129.94     595 2131.91   654.8 2156.67   664.8 2160.49
   674.8 2163.12   694.8 2166.07   714.7 2167.66   794.5  2178.1   834.5 2182.67
#Mann= 3 , 0 , 0
       0     .06       0   407.8    .045       0   422.8     .06       0
Bank Sta=407.8,422.8
XS Rating Curve= 0 ,0
Exp/Cntr=0.3,0.1

Type RM Length L Ch R = 1 ,11997.4 ,409,416.8,424.5
XS GIS Cut Line= 3
     1929101.541      172763.302     1928951.706      172509.235
     1928607.173      171979.835
#Sta/Elev= 30
       0 2149.04     9.8 2146.31    29.5 2142.46    49.2 2136.76      59 2135.44
   147.5 2127.75   167.1 2124.65   226.1 2117.44   314.7 2109.03   393.6 2098.58
   413.4 2093.59   452.9 2081.32   482.5 2076.25   497.3 2075.83   502.2  2075.8
   512.3 2076.09   610.8 2081.05   699.6 2086.45   709.5 2088.24   739.1 2097.52
   758.8 2106.26   778.6 2120.16   788.4 2124.62     818 2135.81   847.6 2144.29
   857.5 2146.09   867.4 2145.94   887.1 2142.61   916.7 2140.59   926.6 2139.18
#Mann= 3 , 0 , 0
       0     .06       0   497.3    .045       0   512.3     .06       0
Bank Sta=497.3,512.3
XS Rating Curve= 0 ,0
Exp/Cntr=0.3,0.1

Type RM Length L Ch R = 1 ,11580.4 ,407.3,396.2,384.1
XS GIS Cut Line= 2
      1929293.72      172857.763     1929062.453      171694.916
#Sta/Elev= 30
       0 2146.99    19.9 2141.86    29.9  2141.8    69.7 2128.15   109.6 2118.83
   119.6  2118.9   159.4 2111.41   189.3 2109.22     259 2107.31   288.9 2110.61
   338.8 2113.49   408.5 2121.13     538 2121.05   567.9 2116.37   617.7  2103.5
   627.7  2102.4   667.5 2085.16   687.5 2078.76   707.4 2076.12   753.6  2074.1
   768.6 2074.14     817 2078.96   986.4 2086.75  1006.3  2094.6  1016.2 2095.04
    1086  2123.3    1096 2124.05  1115.9 2128.78  1135.8 2130.72  1185.6 2142.29
#Mann= 3 , 0 , 0
       0     .06       0   753.6    .045       0   768.6     .06       0
Bank Sta=753.6,768.6
XS Rating Curve= 0 ,0
Exp/Cntr=0.3,0.1

Type RM Length L Ch R = 1 ,11183.8 ,379.8,402.2,417.3
XS GIS Cut Line= 3
     1929524.199      172388.103     1929485.899      172062.988
     1929131.044      171605.943
#Sta/Elev= 30
       0 2139.22    39.7 2131.59    49.6 2131.42    79.4 2125.56     129 2112.82
   138.9 2112.62   158.7 2109.05   198.4 2104.13   297.6 2094.29   347.3 2085.18
   377.2 2077.08   397.2 2074.55   417.2  2074.1   500.4 2074.12   506.9 2074.16
   515.4 2076.18   546.8 2088.57   576.8 2103.85   586.8 2106.12   616.7  2121.8
   666.6  2138.3   676.5 2140.13   686.5 2140.29   706.5 2144.36   726.4 2145.94
   766.3 2153.53   826.2 2162.71   836.2 2163.52   866.1 2162.46     906 2157.87
#Mann= 3 , 0 , 0
       0     .06       0   500.4    .045       0   515.4     .06       0
Bank Sta=500.4,515.4
XS Rating Curve= 0 ,0
Exp/Cntr=0.3,0.1

Type RM Length L Ch R = 1 ,10780.7 ,523.9,510.2,499
XS GIS Cut Line= 3
     1929610.839      172385.821     1929676.221      171980.858
     1929677.987      171519.761
#Sta/Elev= 30
       0 2142.56    19.5 2137.08    48.8 2133.85   107.4 2122.19     127 2119.77
   146.5  2118.7   224.6 2107.68   244.2 2106.49   263.7 2103.54   322.3 2092.05
   332.1 2091.65   390.7 2074.92   402.7 2074.15   410.2  2074.1   417.7  2074.2
   429.8 2074.26   488.7 2082.34   537.8 2086.62   557.4 2092.48   596.6 2108.03
   635.8 2114.86   675.1 2129.22   714.3 2145.64   724.2 2148.77     734 2149.81
   773.2 2166.36   792.8 2172.83   822.2 2178.78   851.7 2180.01   871.3 2179.66
#Mann= 3 , 0 , 0
       0     .06       0   402.7    .045       0   417.7     .06       0
Bank Sta=402.7,417.7
XS Rating Curve= 0 ,0
Exp/Cntr=0.3,0.1

Type RM Length L Ch R = 1 ,10271   ,507.7,512.6,517.8
XS GIS Cut Line= 3
     1930338.373      172127.629     1930161.689       171957.79
     1929851.631       171422.89
#Sta/Elev= 30
       0 2106.39    19.6 2107.54      49 2106.36    68.6 2104.31    88.2 2101.41
      98 2101.42   127.4 2094.83   166.6  2087.6   186.3 2084.62   205.9 2082.76
   245.1 2081.71   294.9 2079.44   404.6 2072.52   424.6 2072.32   434.5  2072.6
   449.5 2073.74   524.3 2079.88   534.3 2082.54   574.2 2099.98   594.1 2104.32
     614 2112.49     634 2117.37   683.8 2127.12   693.8 2127.75   713.8  2132.6
   763.6 2145.84   793.5 2157.25   813.5    2161   833.4 2166.63   863.3 2173.76
#Mann= 3 , 0 , 0
       0     .06       0   434.5    .045       0   449.5     .06       0
Bank Sta=434.5,449.5
XS Rating Curve= 0 ,0
Exp/Cntr=0.3,0.1

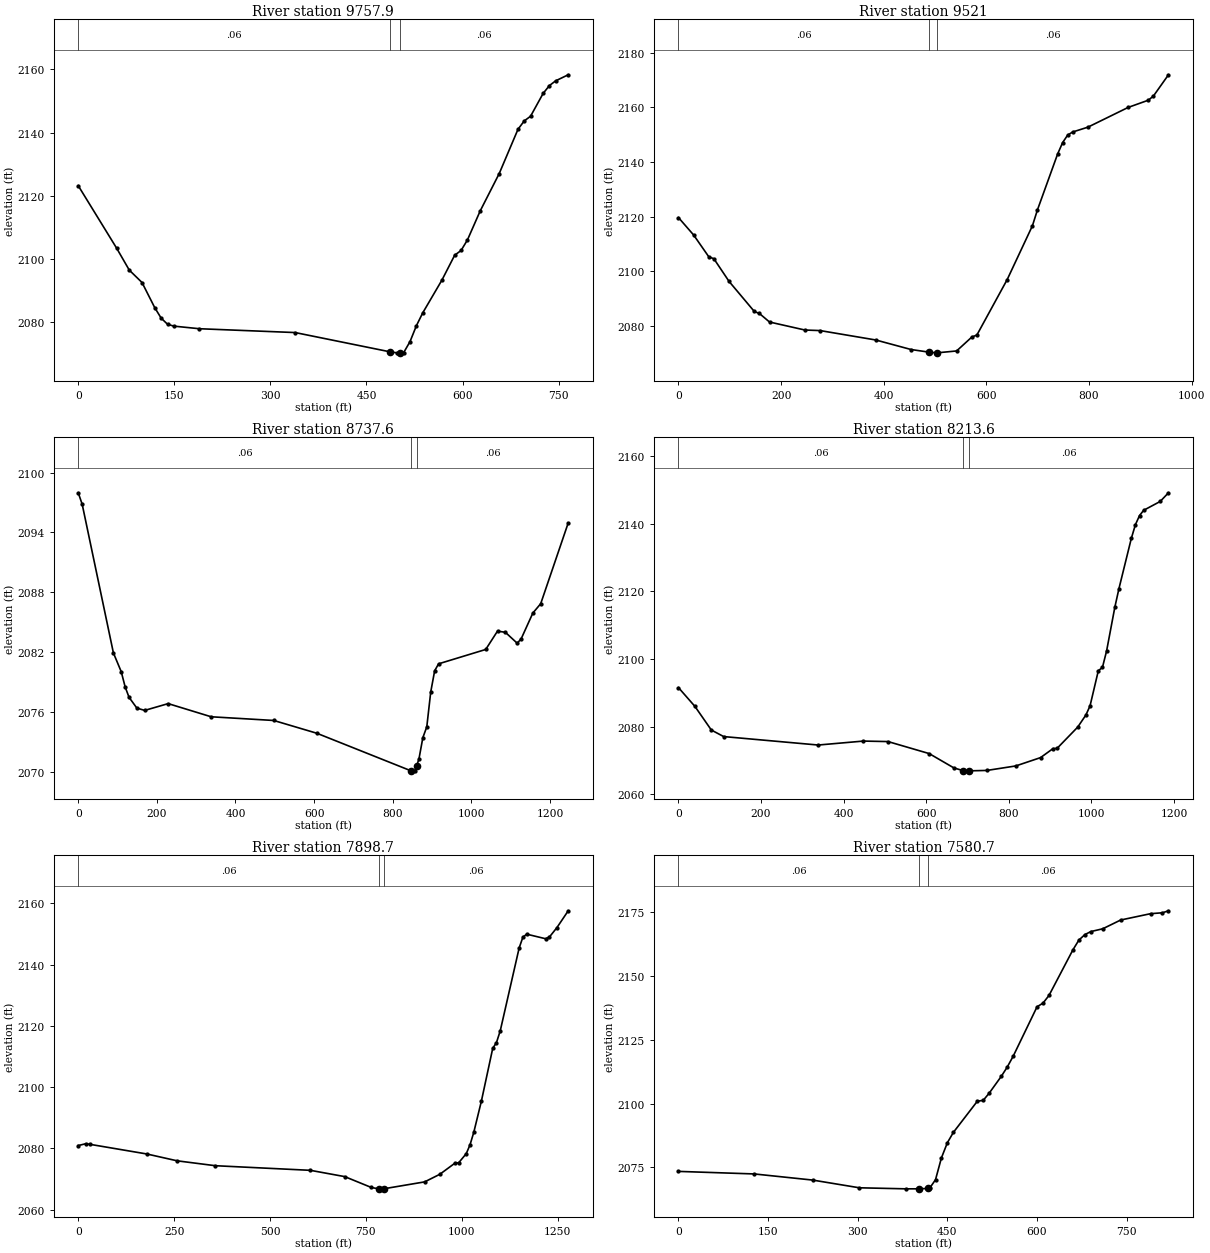
Type RM Length L Ch R = 1 ,9757.9  ,236,236.9,236.3
XS GIS Cut Line= 3
     1930601.007      172061.054      1930437.94      171434.435
     1930430.611      171317.173
#Sta/Elev= 30
       0  2123.2    59.8  2103.5    79.7 2096.51    99.6 2092.59   119.5 2084.62
   129.5 2081.33   139.5 2079.38   149.4  2078.8   189.3 2077.98   338.7 2076.77
   487.5 2070.65   498.1 2070.36   502.5 2070.38     508  2070.4     518 2073.91
     528 2078.95   537.9 2083.01   567.8 2093.35   587.7 2101.21   597.7 2102.72
   607.6 2106.03   627.6 2115.24   657.3 2127.05   686.6 2141.04   696.4 2143.69
   706.2 2145.15   725.8 2152.36   735.6 2154.84   745.4 2156.35     765 2158.26
#Mann= 3 , 0 , 0
       0     .06       0   487.5    .045       0   502.5     .06       0
Bank Sta=487.5,502.5
XS Rating Curve= 0 ,0
Exp/Cntr=0.3,0.1

Type RM Length L Ch R = 1 ,9521    ,775.3,783.1,790.9
XS GIS Cut Line= 3
     1930820.874      172033.571     1930633.979      171420.853
     1930489.145       171141.99
#Sta/Elev= 30
       0 2119.68    29.6  2113.3    59.1 2105.34      69 2104.63    98.6 2096.34
   147.8 2085.35   157.7 2084.62   177.4  2081.5   246.4 2078.57     276 2078.37
   384.4 2074.93   453.3 2071.44   488.7 2070.47   502.6 2070.23   503.7 2070.23
     542 2070.92   571.6    2076   581.5 2076.75   640.6 2097.04   689.7 2116.69
   699.5  2122.5   738.8 2142.92   748.6 2147.11   758.4 2149.85   768.2 2150.98
   797.7 2152.73   876.3 2159.96   915.5 2162.59   925.4  2164.1   954.8 2171.89
#Mann= 3 , 0 , 0
       0     .06       0   488.7    .045       0   503.7     .06       0
Bank Sta=488.7,503.7
XS Rating Curve= 0 ,0
Exp/Cntr=0.3,0.1

Type RM Length L Ch R = 1 ,8737.6  ,515.5,523.6,519.5
XS GIS Cut Line= 3
      1931268.24      171983.185     1931263.507      171406.271
     1931290.227      170737.276
#Sta/Elev= 30
       0 2097.98      10 2096.84    89.5 2081.92   109.4 2080.04   119.4 2078.51
   129.3 2077.47   149.2 2076.39   169.1 2076.16   228.8 2076.84   338.2 2075.52
   497.4 2075.15   606.9 2073.87     846 2070.11   846.7  2070.1   856.7 2070.12
     861 2070.62   866.7 2071.28   876.7 2073.43   886.7 2074.51   896.7    2078
   906.7 2080.13   916.7 2080.83  1036.6 2082.27  1066.6 2084.11  1086.6 2083.99
  1116.6  2082.9  1126.6 2083.32  1156.5 2085.92  1176.5 2086.86  1246.5 2094.96
#Mann= 3 , 0 , 0
       0     .06       0     846    .045       0     861     .06       0
Bank Sta=846,861
XS Rating Curve= 0 ,0
Exp/Cntr=0.3,0.1

Type RM Length L Ch R = 1 ,8213.6  ,330.7,314.3,297.8
XS GIS Cut Line= 3
     1931422.147      171980.742     1931551.623      171377.331
      1931806.34      170867.934
#Sta/Elev= 30
       0  2091.5    39.8 2085.96    79.6 2078.96   109.5 2077.03   338.4 2074.53
   447.9  2075.7   507.6 2075.55   607.2    2072   667.1 2067.76   689.6 2066.95
   704.6  2066.9     747 2067.02     817 2068.35   876.9 2070.81   906.9 2073.46
   916.9 2073.54   966.9 2079.83   986.8 2083.42   996.8 2086.13  1016.8 2096.49
  1026.8 2097.48  1036.8 2102.31  1056.8 2115.26  1066.8 2120.79  1096.8 2135.65
  1106.7 2139.69  1116.7 2142.38  1126.7 2143.93  1166.7 2146.54  1186.7  2149.1
#Mann= 3 , 0 , 0
       0     .06       0   689.6    .045       0   704.6     .06       0
Bank Sta=689.6,704.6
XS Rating Curve= 0 ,0
Exp/Cntr=0.3,0.1

Type RM Length L Ch R = 1 ,7898.7  ,316.5,317.9,320
XS GIS Cut Line= 3
     1932074.416      172056.473     1931786.147      171179.451
     1931819.159      170826.463
#Sta/Elev= 30
       0 2080.93    19.8 2081.52    29.8 2081.34   178.7 2078.18   258.1 2075.94
   357.4 2074.35   605.5 2072.84   694.9 2070.79   764.4 2067.24   783.2 2066.81
   784.2  2066.8   798.2 2066.85   903.3 2069.07   942.9 2071.55   982.3 2075.18
   992.1 2075.32  1011.8 2078.28  1021.7 2081.19  1031.5 2085.28  1051.2 2095.39
  1080.8 2112.63  1090.6 2114.54  1100.4 2118.35  1149.7 2145.39  1159.5 2148.93
  1169.4 2149.91  1218.6 2148.42  1228.5 2148.96  1248.2 2152.04  1277.7 2157.54
#Mann= 3 , 0 , 0
       0     .06       0   783.2    .045       0   798.2     .06       0
Bank Sta=783.2,798.2
XS Rating Curve= 0 ,0
Exp/Cntr=0.3,0.1

Type RM Length L Ch R = 1 ,7580.7  ,397.9,400,399.6
XS GIS Cut Line= 3
     1932199.796      171604.494     1932091.957      171208.861
     1932012.186      170806.866
#Sta/Elev= 30
       0 2073.44   126.9 2072.44   224.6 2070.04   302.7 2067.02   380.8 2066.61
   402.6 2066.62   417.6 2066.76   420.1  2066.8   430.1 2070.19     440 2078.74
     450 2084.69     460 2088.72     500 2100.89     510 2101.27     520  2104.1
     540  2110.6     550 2114.24     560 2118.51     600 2137.89     610 2139.33
     620 2142.34     660 2160.18     670    2164     680 2166.15     690 2167.34
   709.9 2168.43   739.9 2171.86   789.9 2174.34   809.9  2174.7   819.9 2175.48
#Mann= 3 , 0 , 0
       0     .06       0   402.6    .045       0   417.6     .06       0
Bank Sta=402.6,417.6
XS Rating Curve= 0 ,0
Exp/Cntr=0.3,0.1

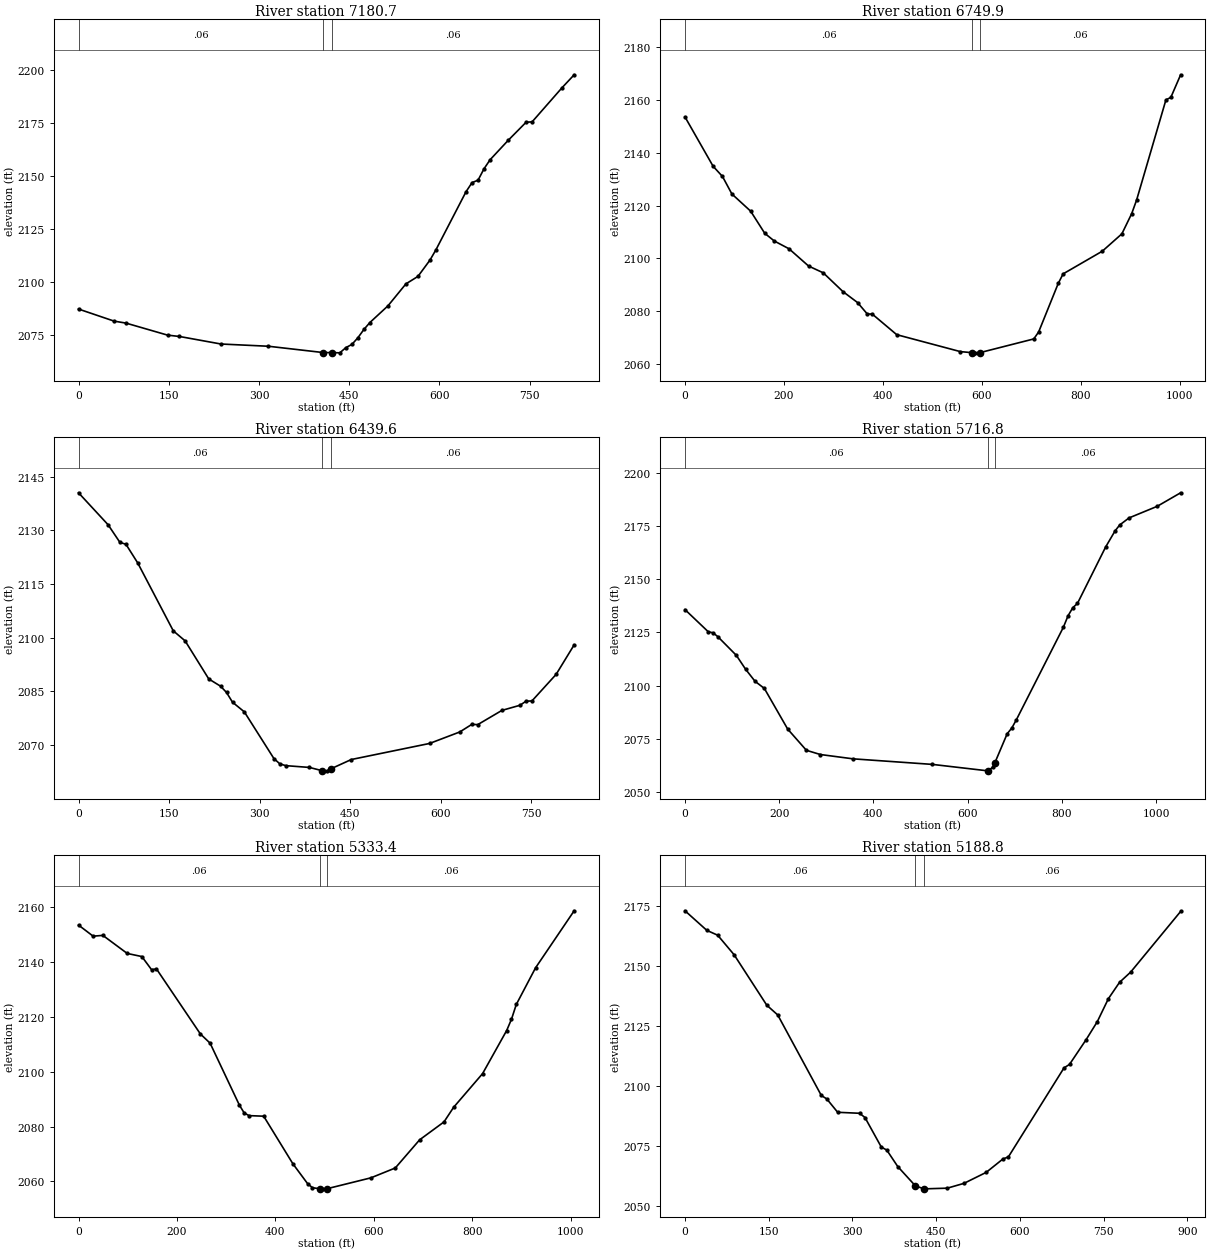
Type RM Length L Ch R = 1 ,7180.7  ,435.2,430.7,427
XS GIS Cut Line= 3
     1932557.919      171570.135     1932486.375      171161.907
     1932400.666      170761.372
#Sta/Elev= 30
       0 2087.27    59.2 2081.56    78.9 2080.63     148 2074.95   167.8 2074.31
   236.8 2070.75   315.8 2069.69   406.9 2066.71   421.9  2066.7   434.4 2066.58
   444.4 2069.03   454.4 2070.54   464.4 2073.68   474.4 2077.61   484.4  2080.9
   514.4 2088.77   544.3 2099.16   564.3 2102.69   584.3  2110.4   594.3 2115.31
   644.2 2142.68   654.2 2146.99   664.2 2148.15   674.2 2153.56   684.2 2157.79
   714.2 2166.94   744.1 2175.53   754.1  2175.7   804.1 2191.91     824 2197.94
#Mann= 3 , 0 , 0
       0     .06       0   406.9    .045       0   421.9     .06       0
Bank Sta=406.9,421.9
XS Rating Curve= 0 ,0
Exp/Cntr=0.3,0.1

Type RM Length L Ch R = 1 ,6749.9  ,303.9,310.3,319.2
XS GIS Cut Line= 3
     1933078.472        171665.6     1933010.069      171509.251
     1932776.129      170712.131
#Sta/Elev= 30
       0 2153.54    56.9 2134.86    75.8 2131.01    94.8 2124.39   132.7 2117.89
   161.2 2109.51   180.6 2106.59   210.2 2103.67   249.8 2097.13   279.4 2094.57
     319  2087.5   348.7 2083.32   368.4 2078.99   378.3 2078.98   427.8 2071.18
   556.4 2064.77   580.4 2064.37     586 2064.31   595.4 2064.36   704.7 2069.57
   714.6 2072.23   754.2  2090.6     764 2094.18   843.2 2102.76   882.7 2109.32
   902.5 2116.95   912.4 2122.07   971.7 2160.01   981.6 2160.92  1001.4 2169.48
#Mann= 3 , 0 , 0
       0     .06       0   580.4    .045       0   595.4     .06       0
Bank Sta=580.4,595.4
XS Rating Curve= 0 ,0
Exp/Cntr=0.3,0.1

Type RM Length L Ch R = 1 ,6439.6  ,707.9,722.5,733.9
XS GIS Cut Line= 3
     1933216.253      171489.694     1933186.168      171078.772
     1933206.099      170670.203
#Sta/Elev= 30
       0 2140.47      49 2131.54    68.7 2126.59    78.5 2126.11    98.1 2120.87
     157 2101.91   176.6 2099.11   215.8 2088.47   235.4 2086.44   245.2  2084.7
   255.1 2081.98   274.7 2079.28   323.7 2066.24   333.5 2064.76   343.4 2064.26
   382.6 2063.76   402.9 2062.88     412 2062.81   417.9 2063.36   451.9 2065.97
   581.6 2070.46   631.5 2073.66   651.5 2075.78   661.4 2075.72   701.4 2079.69
   731.3 2081.12   741.3 2082.26   751.2 2082.34   791.2 2089.75   821.1    2098
#Mann= 3 , 0 , 0
       0     .06       0   402.9    .045       0   417.9     .06       0
Bank Sta=402.9,417.9
XS Rating Curve= 0 ,0
Exp/Cntr=0.3,0.1

Type RM Length L Ch R = 1 ,5716.8  ,381.6,382.9,384.2
XS GIS Cut Line= 3
     1933540.191      171565.439      1933845.56      170942.485
     1934082.527      170673.759
#Sta/Elev= 30
       0 2135.77    49.6  2125.3    59.5 2124.85    69.4  2123.1     109 2114.24
   128.8 2107.66   148.7 2102.02   168.5 2098.66     218 2079.53   257.7 2069.54
   287.4 2067.55   356.8 2065.52   525.3  2062.9   642.3 2059.88   644.2 2059.87
   654.1 2061.82   657.3  2063.4   683.9 2077.32   693.8 2080.04   703.7 2084.03
   803.2 2127.46   813.2 2132.89   823.2 2136.66   833.1 2138.68   892.8 2165.19
   912.7 2172.74   922.7 2175.59   942.6 2178.93  1002.3 2184.38  1052.1 2190.76
#Mann= 3 , 0 , 0
       0     .06       0   642.3    .045       0   657.3     .06       0
Bank Sta=642.3,657.3
XS Rating Curve= 0 ,0
Exp/Cntr=0.3,0.1

Type RM Length L Ch R = 1 ,5333.4  ,145.8,143.6,149
XS GIS Cut Line= 3
     1933713.641      171748.661     1934077.641      171101.277
     1934239.703      170892.301
#Sta/Elev= 30
       0 2153.43    29.7 2149.39    49.5 2149.67      99 2143.09   128.7 2141.96
   148.5 2137.16   158.4 2137.46   247.6 2113.76   267.4 2110.39   326.8 2087.86
   336.7 2084.95   346.6 2083.99   376.3 2083.78   435.7 2066.42   465.4 2059.23
   475.3 2057.72   490.1 2057.36   495.1 2057.31   505.1 2057.36   594.2 2061.32
   643.7 2064.91   693.2 2075.18   742.7  2081.7   762.3 2087.04   821.1  2099.3
     870 2114.99   879.8  2119.1   889.6  2124.5   928.8 2137.87  1007.2 2158.64
#Mann= 3 , 0 , 0
       0     .06       0   490.1    .045       0   505.1     .06       0
Bank Sta=490.1,505.1
XS Rating Curve= 0 ,0
Exp/Cntr=0.3,0.1

Type RM Length L Ch R = 1 ,5188.8  ,473.8,478.9,474.9
XS GIS Cut Line= 3
     1933938.911      171762.182     1934080.184      171366.384
     1934314.139      170961.205
#Sta/Elev= 30
       0 2173.03    39.1 2164.89    58.6 2162.86      88 2154.74   146.6 2133.72
   166.2 2129.67   244.3 2096.16   254.1 2094.72   273.6 2089.16   312.8 2088.75
   322.5 2086.99   351.8 2074.68   361.6 2073.43   381.2 2066.59   412.8 2058.55
   427.8 2057.32   430.2  2057.3     470 2057.58   499.9 2059.58   539.7 2064.15
   569.6 2069.71   579.5  2070.6   679.1 2107.63     689 2109.09   718.9 2119.44
   738.8 2126.89   758.7 2136.46   778.6 2143.24   798.5 2147.49   888.1 2172.75
#Mann= 3 , 0 , 0
       0     .06       0   412.8    .045       0   427.8     .06       0
Bank Sta=412.8,427.8
XS Rating Curve= 0 ,0
Exp/Cntr=0.3,0.1