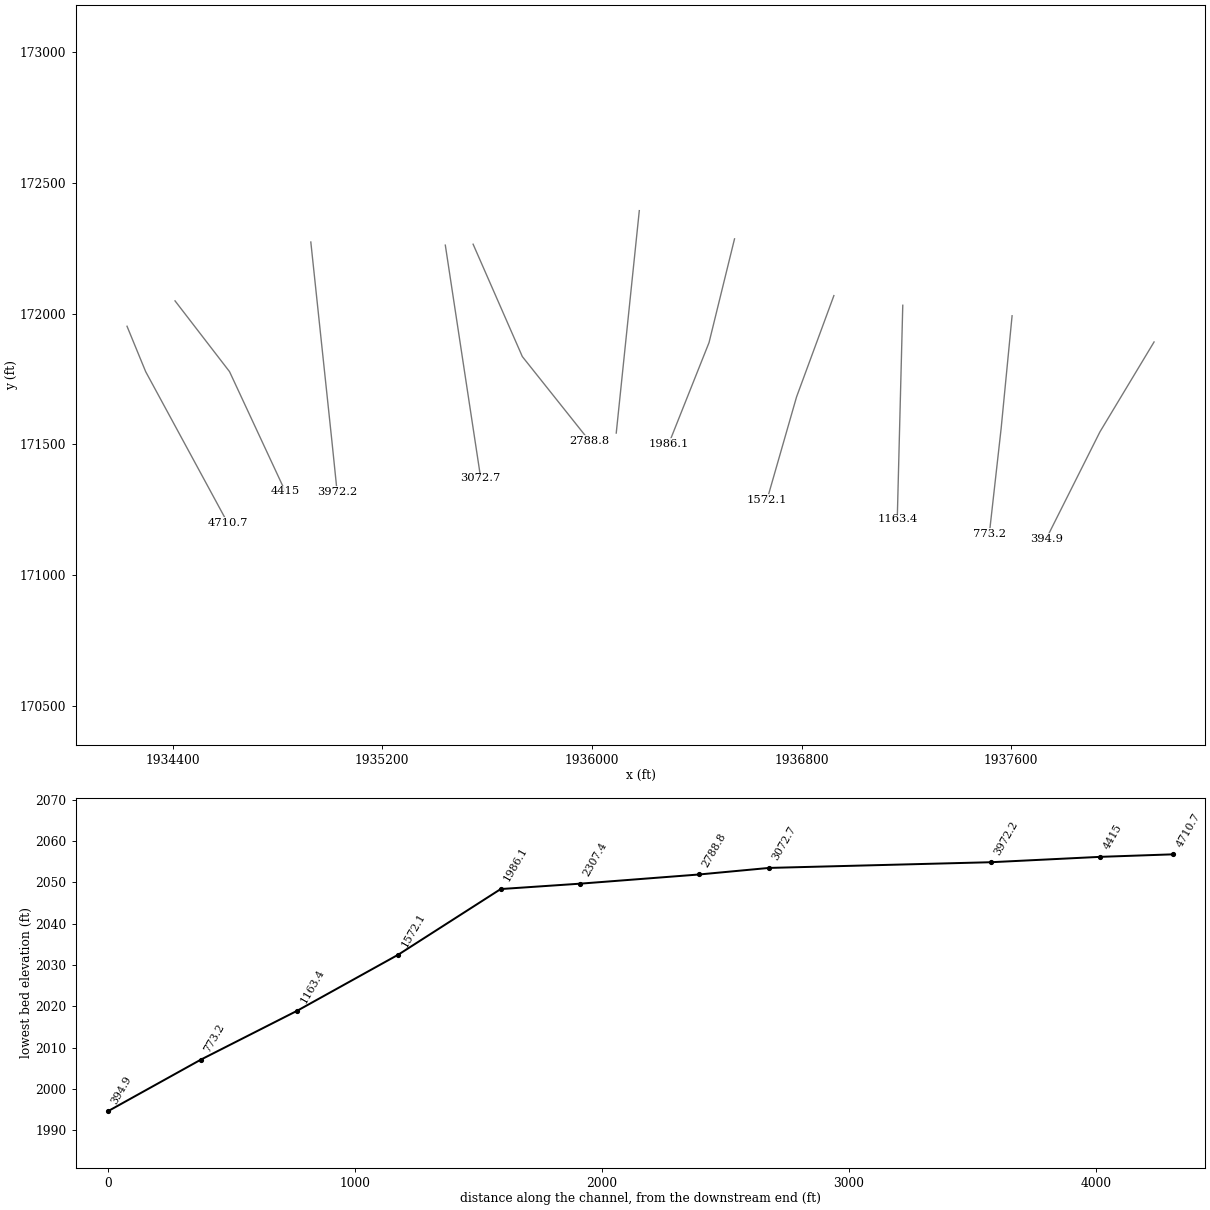
HEC-RAS study WlfCrk.prj: WlfCrk

--- WlfCrk.g01 (geometry) --- (continued)

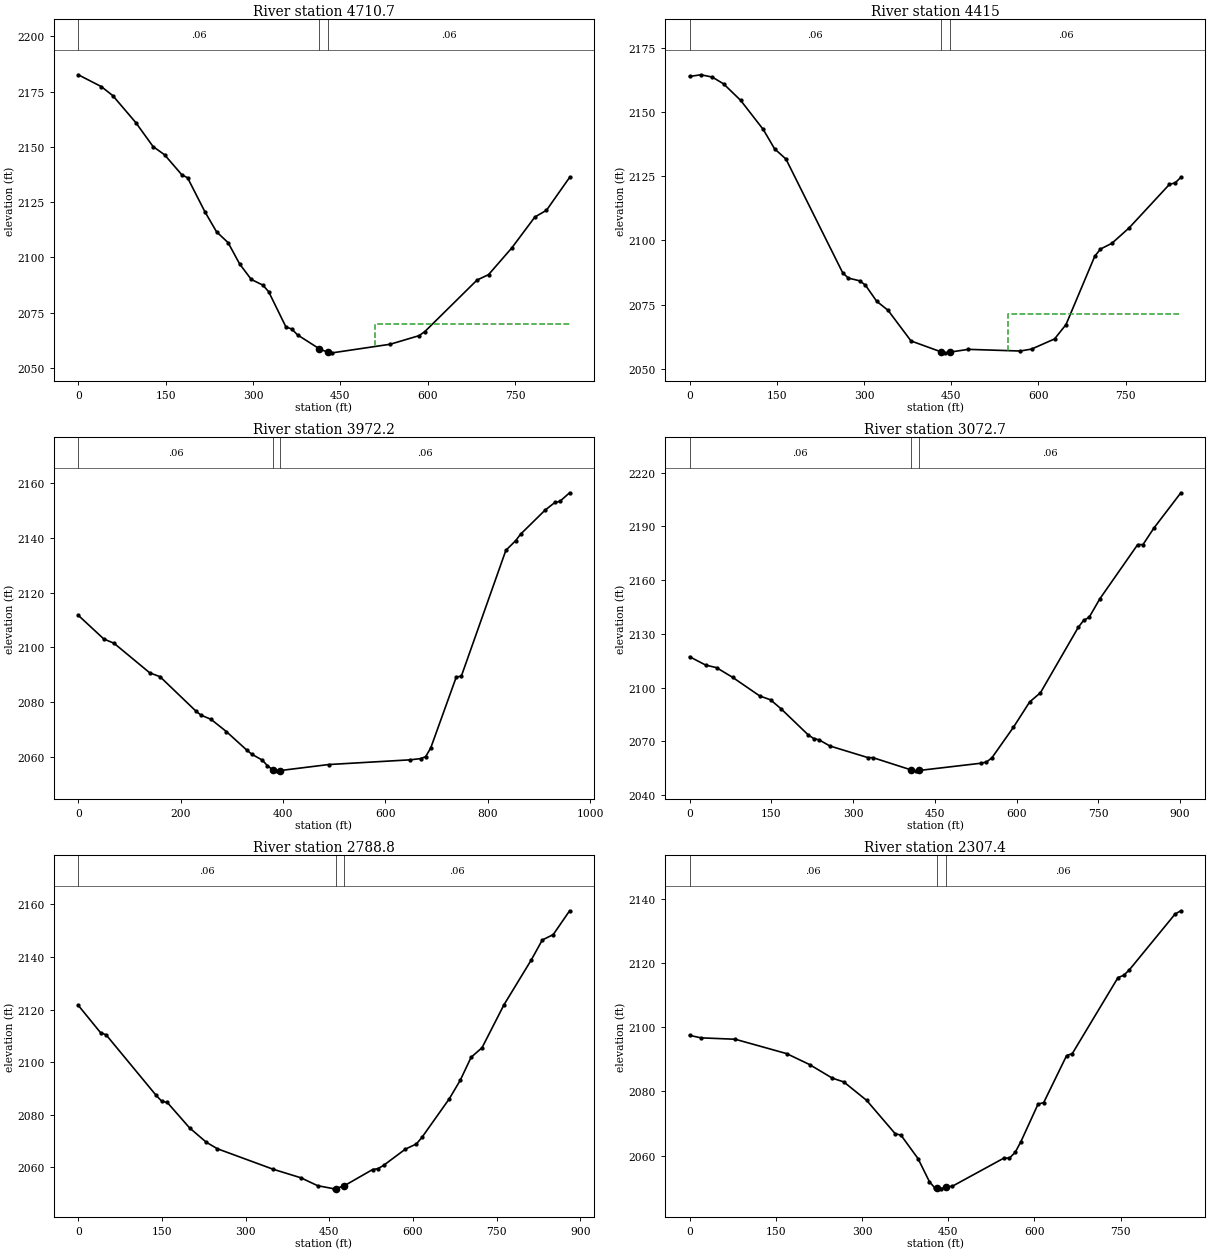
Type RM Length L Ch R = 1 ,4710.7  ,299.7,295.6,291.8
XS GIS Cut Line= 3
     1934226.307      171951.552     1934297.508      171777.976
     1934609.652      171201.234
#Sta/Elev= 30
       0 2182.66    39.5 2177.31    59.2 2173.23    98.7 2161.01   128.4 2150.15
   148.1 2146.44   177.7 2137.38   187.6 2136.01   217.4  2120.6   237.3 2111.57
   257.2 2106.63     277 2096.98   296.9    2090   316.8 2087.42   326.7 2084.47
   356.5 2068.44   366.5 2067.54   376.4 2064.87     414 2058.54     429 2056.92
     436 2056.75   535.4 2060.64   585.1 2064.54     595  2066.4   684.4 2089.69
   704.3 2092.17     744 2104.21   783.8 2118.26   803.7  2121.3   843.4 2136.19
#Mann= 3 , 0 , 0
       0     .06       0     414    .045       0     429     .06       0
#XS Ineff= 2 , 0
                          509.98         2069.81
Permanent Ineff=
       F       F
Bank Sta=414,429
XS Rating Curve= 0 ,0
Exp/Cntr=0.3,0.1

Type RM Length L Ch R = 1 ,4415    ,450.9,442.7,433.9
XS GIS Cut Line= 3
     1934409.481      172048.639     1934617.535      171777.976
     1934829.738      171321.212
#Sta/Elev= 30
       0 2164.04    19.5  2164.7      39 2163.81    58.5 2161.16    87.8 2154.74
   126.8 2143.34   146.3 2135.78   165.8 2131.81   263.4  2087.4   273.1 2085.33
   292.6 2084.26   302.4  2082.6   321.9 2076.27   341.4 2072.75   380.9 2060.79
   432.8  2056.5   440.1 2056.14   447.8 2056.42   479.6  2057.5   568.5 2056.85
   588.3 2057.61   627.8 2061.57   647.5 2067.18   696.9 2093.84   706.8 2096.67
   726.5 2098.92   756.2 2104.96   825.3  2121.9   835.2  2122.5     845 2124.66
#Mann= 3 , 0 , 0
       0     .06       0   432.8    .045       0   447.8     .06       0
#XS Ineff= 2 , 0
                          548.39         2071.25
Permanent Ineff=
       F       F
Bank Sta=432.8,447.8
XS Rating Curve= 0 ,0
Exp/Cntr=0.3,0.1

Type RM Length L Ch R = 1 ,3972.2  ,898.3,898.8,896.5
XS GIS Cut Line= 3
     1934927.634      172273.599     1935008.408      171509.251
     1935027.952        171318.7
#Sta/Elev= 30
       0 2111.73    49.9 2103.07    69.9  2101.5   139.8 2090.67   159.7 2089.29
   229.6 2076.74   239.6 2075.24   259.5 2073.67   289.5 2069.19   329.4  2062.4
   339.4 2060.88   359.4 2058.79   369.3 2056.79   380.1 2055.17   389.3 2054.84
   395.1 2054.96   489.1 2057.14   648.8 2058.87   668.8 2059.31   678.8 2060.01
   688.8 2063.22   738.7 2089.16   748.6 2089.47   835.6  2135.5   854.8 2139.05
   864.4 2141.41   912.3 2150.22   931.4 2153.01     941  2153.4   960.2 2156.56
#Mann= 3 , 0 , 0
       0     .06       0   380.1    .045       0   395.1     .06       0
Bank Sta=380.1,395.1
XS Rating Curve= 0 ,0
Exp/Cntr=0.3,0.1

Type RM Length L Ch R = 1 ,3072.7  ,281.3,283.9,295
XS GIS Cut Line= 2
     1935440.812      172261.682     1935575.966      171370.509
#Sta/Elev= 30
       0  2117.2    29.7 2112.51    49.5 2111.09    79.2 2105.64   128.8 2095.28
   148.6 2093.13   168.4 2087.97   217.9 2073.49   227.8 2071.51   237.7 2070.76
   257.5 2067.34   326.9 2060.89   336.8 2060.79   406.3    2054     416 2053.46
   421.3 2053.67   534.9 2057.72   544.8 2058.39   554.7 2060.72   594.3 2077.82
     624 2091.93   643.8 2097.06   713.2  2133.6   723.1 2137.52     733 2139.12
   752.8 2149.54   822.1 2179.76     832 2179.84   851.8 2188.97   901.4 2208.74
#Mann= 3 , 0 , 0
       0     .06       0   406.3    .045       0   421.3     .06       0
Bank Sta=406.3,421.3
XS Rating Curve= 0 ,0
Exp/Cntr=0.3,0.1

Type RM Length L Ch R = 1 ,2788.8  ,489.6,481.2,464.3
XS GIS Cut Line= 3
      1935546.88      172265.243     1935734.716      171835.653
     1935991.196      171512.982
#Sta/Elev= 30
       0 2121.61    39.9 2111.23    49.9 2110.41   139.7 2087.37   149.6 2085.19
   159.6 2084.69   199.5 2075.05   229.4  2069.6   249.4 2067.11   349.2 2059.33
     399 2056.08     429 2053.08   458.9 2051.87   461.4 2051.96   476.4 2052.97
   527.7  2059.2   537.6 2059.57   547.4 2060.78   586.6 2066.98   606.3 2068.93
   616.1  2071.4   665.1 2086.05   684.8  2093.1   704.4 2101.88     724 2105.52
   763.3 2121.82   812.4 2138.92     832 2146.45   851.6  2148.5     881 2157.56
#Mann= 3 , 0 , 0
       0     .06       0   461.4    .045       0   476.4     .06       0
Bank Sta=461.4,476.4
XS Rating Curve= 0 ,0
Exp/Cntr=0.3,0.1

Type RM Length L Ch R = 1 ,2307.4  ,324.4,321.2,315
XS GIS Cut Line= 2
     1936181.028      172393.601     1936093.025      171543.246
#Sta/Elev= 30
       0 2097.42    19.9 2096.65    79.5 2096.21     169 2091.74   208.8 2088.34
   248.5  2084.1   268.4 2082.93   308.2 2077.18   357.9  2066.8   367.8 2066.38
   397.6 2059.06   417.5 2051.84   427.4 2049.83   430.8 2049.77   437.4 2049.65
   445.8 2050.24   457.3 2050.46   546.7 2059.19   556.7 2059.23   566.6 2060.99
   576.6 2064.35   606.4 2076.01   616.3 2076.51   656.1 2091.12     666 2091.74
   745.6 2115.42   755.5  2116.1   765.4 2117.84     845 2135.21   854.9  2136.2
#Mann= 3 , 0 , 0
       0     .06       0   430.8    .045       0   445.8     .06       0
Bank Sta=430.8,445.8
XS Rating Curve= 0 ,0
Exp/Cntr=0.3,0.1

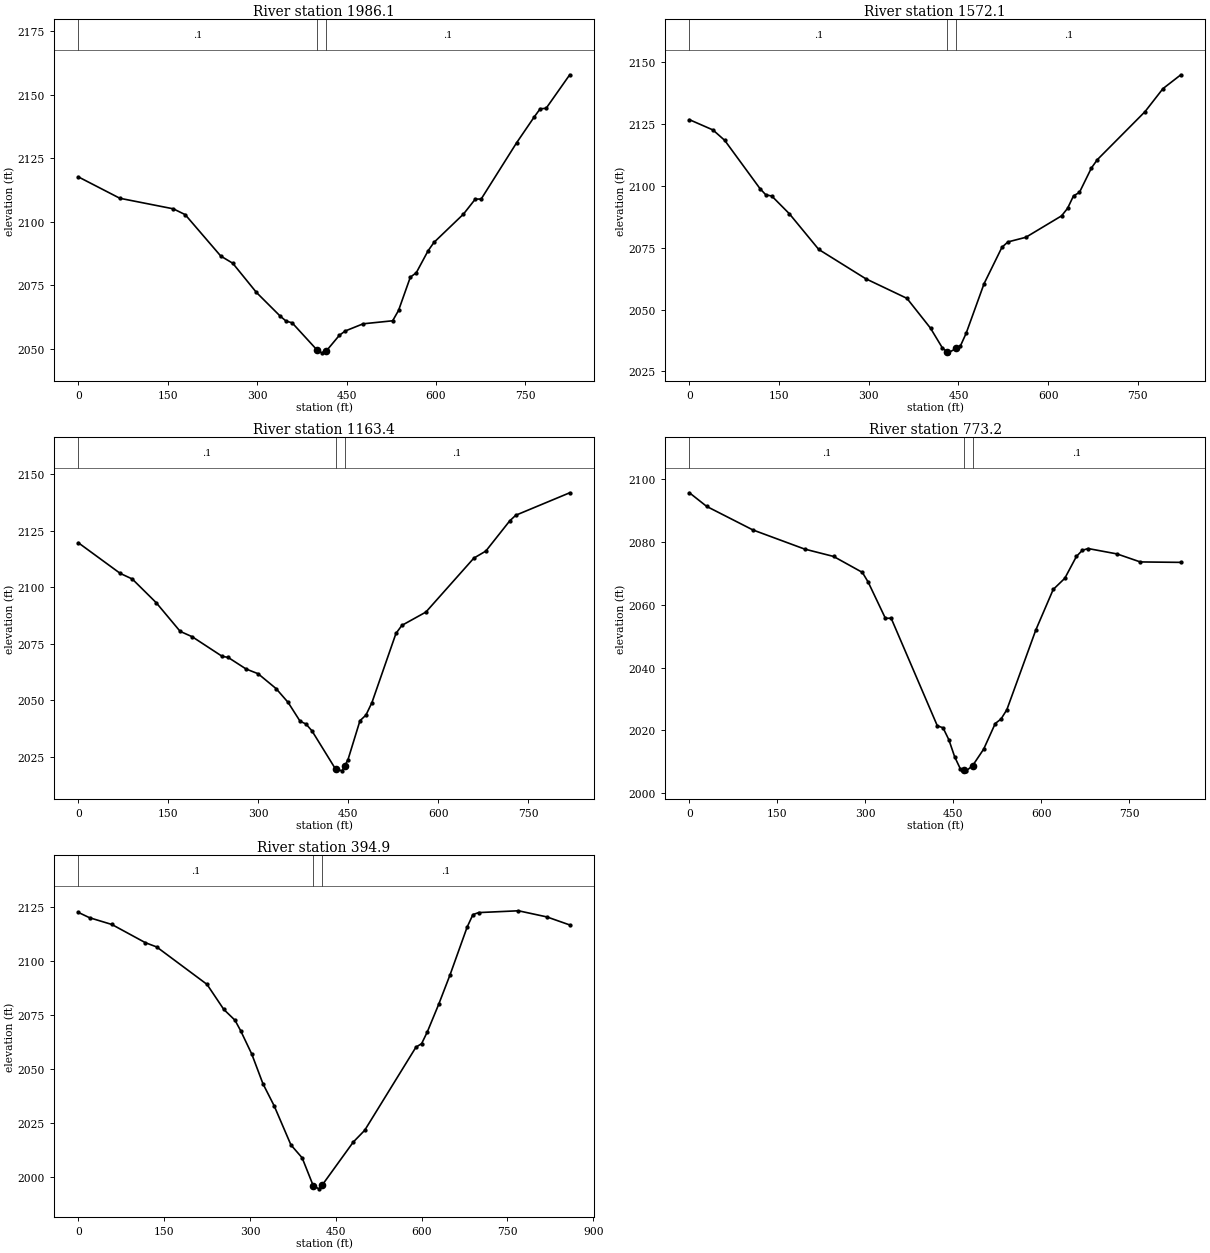
Type RM Length L Ch R = 1 ,1986.1  ,414.5,414.1,416.7
XS GIS Cut Line= 3
     1936544.365      172285.715     1936447.086       171889.12
     1936293.535      171502.657
#Sta/Elev= 30
       0 2117.69    69.7 2109.25   159.4 2105.09   179.3  2102.8     239 2086.47
     259 2083.66   298.8 2072.14   338.6 2062.82   348.6 2060.84   358.6 2060.19
   400.9 2049.34   408.4 2048.35   415.9 2049.08     438  2055.3     448 2056.99
   477.7 2059.79   527.2 2060.98   537.1 2065.05   556.9 2078.18   566.8 2079.88
   586.6 2088.54   596.5 2091.86     646 2103.02   665.8 2108.92   675.7 2108.95
   735.1 2131.11   764.8 2141.34   774.7 2144.52   784.6 2144.69   824.2 2157.91
#Mann= 3 , 0 , 0
       0      .1       0   400.9    .045       0   415.9      .1       0
Bank Sta=400.9,415.9
XS Rating Curve= 0 ,0
Exp/Cntr=0.3,0.1

Type RM Length L Ch R = 1 ,1572.1  ,403,408.7,414.4
XS GIS Cut Line= 3
     1936923.493      172068.755     1936780.949      171681.151
     1936668.353      171288.074
#Sta/Elev= 30
       0 2126.81    39.3 2122.66      59 2118.45     118 2098.94   127.8  2096.4
   137.7 2095.93   167.2 2088.74   216.3 2074.32     295 2062.46   363.8 2054.54
   403.2 2042.48     423 2034.52   431.3 2032.83   432.9  2032.5   446.3 2034.33
   452.9 2035.12   462.8  2040.4   492.8 2060.48   522.7  2075.2   532.7 2077.36
   562.6 2079.23   622.4 2087.91   632.4 2090.93   642.4    2096   652.3 2097.39
   672.3 2107.25   682.2 2110.63     762 2130.06     792 2139.37   821.9 2144.97
#Mann= 3 , 0 , 0
       0      .1       0   431.3    .045       0   446.3      .1       0
Bank Sta=431.3,446.3
XS Rating Curve= 0 ,0
Exp/Cntr=0.3,0.1

Type RM Length L Ch R = 1 ,1163.4  ,392.1,390.2,388.3
XS GIS Cut Line= 3
      1937186.34      172031.868     1937175.811      171622.503
     1937165.281      171213.139
#Sta/Elev= 30
       0  2119.6    69.9 2106.07    89.9 2103.61   129.8 2093.16   169.8 2080.49
   189.8 2078.13   239.7 2069.49   249.7    2069   279.7 2063.88   299.6 2061.81
   329.6 2055.25   349.6 2049.17   369.6 2040.85   379.5 2039.61   389.5 2036.56
   428.7 2019.74   439.5 2018.95   443.7 2021.02   449.4 2023.83   469.4 2041.06
   479.4 2043.55   489.4 2049.09   529.4 2079.57   539.3 2083.14   579.3 2089.01
   659.2 2112.81   679.2 2115.93   719.1 2129.28   729.1 2131.74     819 2141.65
#Mann= 3 , 0 , 0
       0      .1       0   428.7    .045       0   443.7      .1       0
Bank Sta=428.7,443.7
XS Rating Curve= 0 ,0
Exp/Cntr=0.3,0.1

Type RM Length L Ch R = 1 ,773.2   ,386.8,378.3,370.2
XS GIS Cut Line= 3
     1937603.442      171991.649     1937561.706       171561.29
     1937516.632      171158.425
#Sta/Elev= 30
       0  2095.7    29.5 2091.35   108.1 2083.87   196.5 2077.76   245.7 2075.42
   294.8 2070.34   304.6  2067.3   334.1 2055.71   343.9 2055.75   422.6 2021.48
   432.4 2020.82   442.3 2017.02   452.2 2011.59     462  2007.7   467.7 2007.37
   471.9 2007.12   482.7 2008.75   501.6 2014.02   521.4  2022.2   531.2 2023.62
   541.1 2026.57   590.6 2052.02   620.2  2064.9     640 2068.47   659.8 2075.43
   669.7 2077.35   679.6 2077.94     729 2076.22   768.6 2073.67   837.8 2073.53
#Mann= 3 , 0 , 0
       0      .1       0   467.7    .045       0   482.7      .1       0
Bank Sta=467.7,482.7
XS Rating Curve= 0 ,0
Exp/Cntr=0.3,0.1

Type RM Length L Ch R = 1 ,394.9   ,385.1,394.6,403.7
XS GIS Cut Line= 3
      1938145.19      171891.506     1937938.638      171547.823
     1937733.611      171138.501
#Sta/Elev= 30
       0 2122.58    19.6 2120.11    58.7 2116.97   117.4 2108.52   136.9 2106.59
   224.9 2089.25   254.3 2077.63   273.8 2072.65   283.6 2067.85   303.2 2056.94
   322.7 2043.22   342.3    2033   371.6  2014.9   391.2 2008.92   410.8 1995.86
   420.9 1994.57   425.8 1996.15   480.6 2016.25   500.5 2021.67   590.1 2060.18
     600 2061.81     610 2067.28   629.9 2080.06   649.8 2093.76   679.6 2115.81
   689.6 2121.53   699.5 2122.48   769.2 2123.32     819 2120.47   858.8 2116.76
#Mann= 3 , 0 , 0
       0      .1       0   410.8    .045       0   425.8      .1       0
Bank Sta=410.8,425.8
XS Rating Curve= 0 ,0
Exp/Cntr=0.3,0.1

Chan Stop Cuts=-1
Use User Specified Reach Order=0
Composite Channel Slope=5